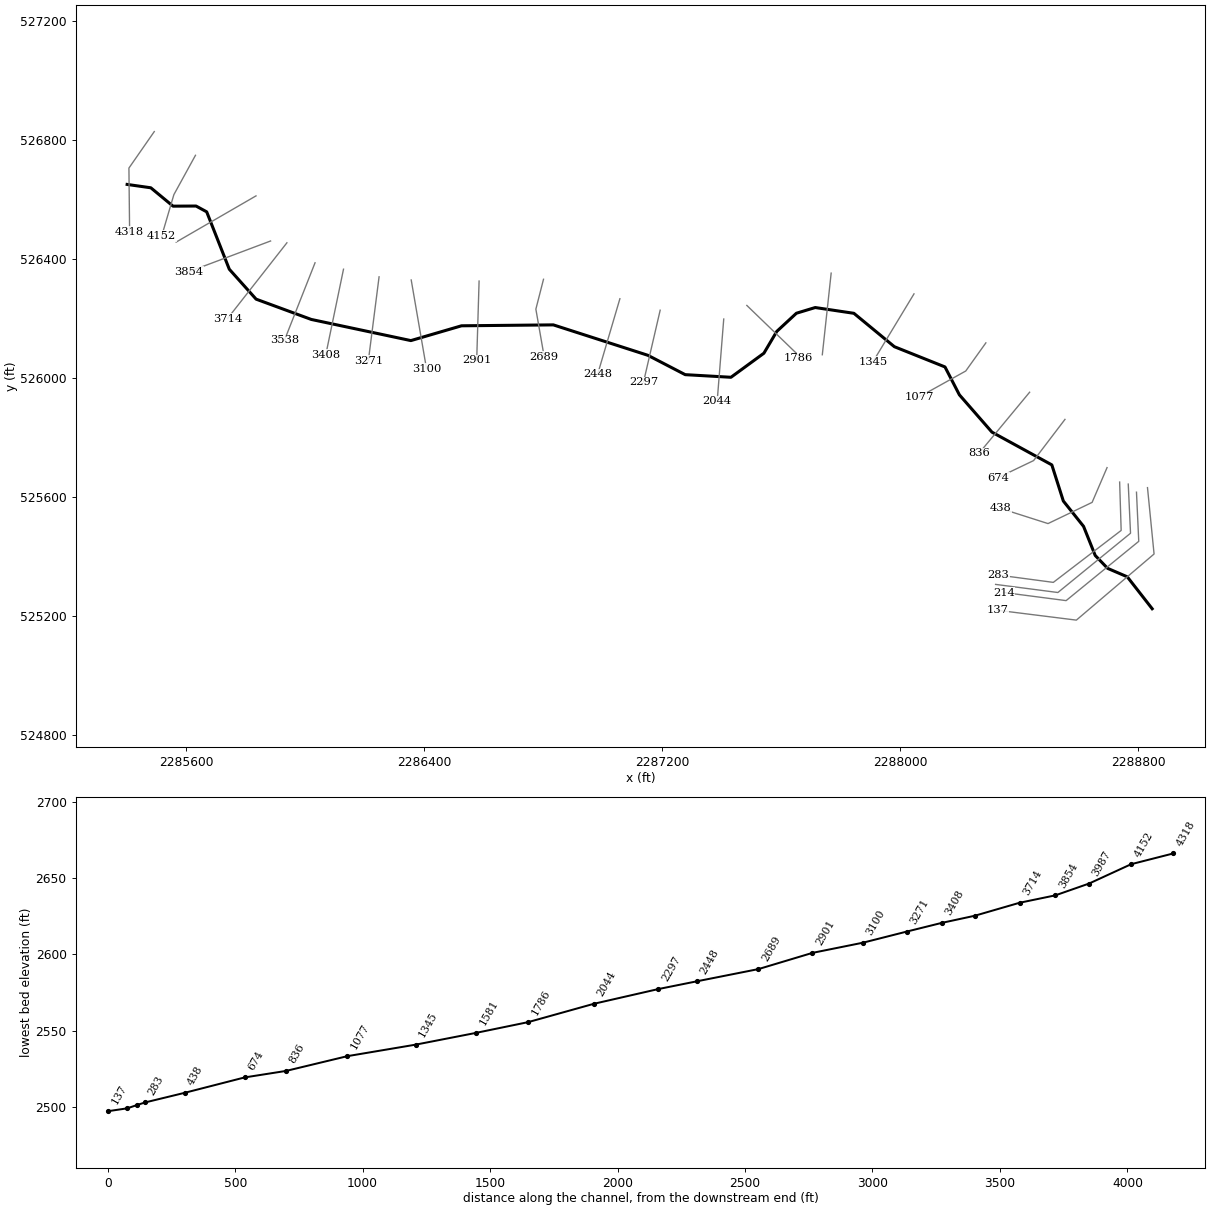
--- WANLESSRN.prj (project) ---

Proj Title=WANLESSRN
Current Plan=p01
Default Exp/Contr=0,0
English Units
Geom File=g01
Flow File=f01
Plan File=p01
Background Map Layer=Inundation Boundary (01pct Value_0)
BEGIN DESCRIPTION:
----------MODEL BY WOOD PLC 2021----------
Stream Name: Wanless Run
Flood Zone: Enhanced Approximate
Pocahontas County, WV
HEC-RAS Version: RAS 6.1
Vertical Datum: NAVD88
Projection: NAD 1983 StatePlane West Virginia S FIPS 4702 (US Feet)
Terrain: 1-meter LIDAR (FEMA Region III 3DEP collected 2016-2018)
Land Use: 2019 NLCD
Hydrologic Method:
WV SIR2010-5033 regression equations
Model Notes:
Normal depth tie in to Greenbrier River
END DESCRIPTION:
DSS Export Rating Curves= 0
DSS Export Rating Curve Sorted= 0
DSS Export Volume Flow Curves= 0
DXF OffsetX= 0
DXF OffsetY= 0
DXF ScaleX= 0
DXF ScaleY= 0

--- WANLESSRN.p01 (plan) ---

Plan Title=Floodplain
Program Version=6.10
Short Identifier=Floodplain
Geom File=g01
Flow File=f01
Subcritical Flow
K Sum by GR= 0
Std Step Tol= 0.01
Critical Tol= 0.01
Num of Std Step Trials= 20
Max Error Tol= 0.3
Flow Tol Ratio= 0.001
Split Flow NTrial= 30
Split Flow Tol= 0.02
Split Flow Ratio= 0.02
Log Output Level= 0
Friction Slope Method= 1
Unsteady Friction Slope Method= 2
Unsteady Bridges Friction Slope Method= 1
Parabolic Critical Depth
Global Vel Dist= 0 , 0 , 0
Global Log Level= 0
CheckData=True
Encroach Param=-1 ,0,0, 0
BEGIN DESCRIPTION:
END DESCRIPTION:
Mapping Interval=1HOUR
Computation Time Step Use Courant=        0
Computation Time Step Use Time Series=    0
Computation Time Step Count To Double=0
Computation Time Step Max Doubling=0
Computation Time Step Max Halving=0
Computation Time Step Residence Courant=0
Run HTab= 0
Run UNet= 0
Run Sediment= 0
Run PostProcess= 0
Run WQNet= 0
Run RASMapper=-1
UNET Theta= 0
UNET Theta Warmup= 0
UNET ZTol= 0
UNET ZSATol= 0
UNET MxIter= 0
UNET Max Iter WO Improvement= 0
UNET MaxInSteps= 0
UNET DtIC= 0
UNET DtMin= 0
UNET MaxCRTS= 0
UNET WFStab= 0
UNET SFStab= 0
UNET WFX= 1
UNET SFX= 1
UNET Gravity=32.174
UNET 1D Methodology=Finite Difference
UNET DSS MLevel= 1
UNET Pardiso=0
UNET DZMax Abort= 0
UNET Use Existing IB Tables= 0
UNET Froude Reduction=False
UNET Froude Limit= 0
UNET Froude Power= 0
UNET D1 Cores= 0
UNET WindReference=Eulerian
UNET WindDragFormulation=Hsu (1988)
UNET D2 Coriolis=0
UNET D2 Cores= 0
UNET D2 Theta= 1
UNET D2 Theta Warmup= 1
UNET D2 Z Tol= 0.01
UNET D2 Volume Tol= 0.01
UNET D2 Max Iterations= 20
UNET D2 Equation= 0
UNET D2 RampUpFraction=0.1
UNET D2 TimeSlices= 1
UNET D2 Turbulence Formulation=Non-Conservative (original)
UNET D2 Eddy Viscosity=0.3
UNET D2 Transverse Eddy Viscosity=0.1
UNET D2 Smagorinsky Mixing=0
UNET D2 BCVolumeCheck=0
UNET D2 Cores=0
UNET D2 SolverType=PARDISO (Direct)
UNET D2 Minimum Iterations= 2147483647
UNET D2 Maximum Iterations= 2147483647
UNET D2 Restart Number= 10
UNET D2 Relaxation Coeff=1.3
UNET D2 SOR Precondition Iterations= 10
UNET D2 ILUT Maximum Fill= 8
UNET D2 ILUT Tolerance=1E-08
UNET D1D2 MaxIter= 0
UNET D1D2 ZTol=0.01
UNET D1D2 QTol=0.1
UNET D1D2 MinQTol=1
Write IC File= 0
Write IC File at Fixed DateTime=0
Write IC File at Sim End=0
Echo Input=False
Echo Parameters=False
Echo Output=False
Write Detailed= 0
HDF Write Warmup=0
HDF Write Time Slices=0
HDF Flush=0
HDF Compression= 1
HDF Chunk Size= 1
HDF Spatial Parts= 1
HDF Use Max Rows=0
HDF Fixed Rows= 1
Calibration Method= 0
Calibration Iterations= 20
Calibration Max Change=0.05
Calibration Tolerance=0.2
Calibration Maximum=1.5
Calibration Minimum=0.5
Calibration Optimization Method= 1
WQ AD Non Conservative
WQ ULTIMATE=-1
WQ Max Comp Step=1HOUR
WQ Output Interval=15MIN
WQ Output Selected Increments= 0
WQ Output face flow=0
WQ Output face velocity=0
WQ Output face area=0
WQ Output face dispersion=0
WQ Output cell volume=0
WQ Output cell surface area=0
WQ Output cell continuity=0
WQ Output cumulative cell continuity=0
WQ Output face conc=0
WQ Output face dconc_dx=0
WQ Output face courant=0
WQ Output face peclet=0
WQ Output face adv mass=0
WQ Output face disp mass=0
WQ Output cell mass=0
WQ Output cell source sink temp=0
WQ Output nsm pathways=0
WQ Output nsm derived pathways=0
WQ Create Restart=0
WQ Fixed Restart=0
WQ System Summary=0
WQ Write To DSS=0
Sorting and Armoring Iterations= 10
XS Update Threshold= 0.02
Bed Roughness Predictor= 0
Hydraulics Update Threshold= 0.02
Energy Slope Method= 1
Volume Change Method= 1
Sediment Retention Method= 0
Sediment TS Multiplier= 1
Warm Up Method= 0
XS Weighting Method= 0
Number of US Weighted Cross Sections= 1
Number of DS Weighted Cross Sections= 1
Upstream XS Weight=0
Main XS Weight=1
Downstream XS Weight=0
Number of DS XS's Weighted with US Boundary= 1
Upstream Boundary Weight= 1
Weight of XSs Associated with US Boundary= 0
Number of US XS's Weighted with DS Boundary= 1
Downstream Boundary Weight= 0.5
Weight of XSs Associated with DS Boundary= 0.5
Percentile Method= 0
Sediment Output Level= 3
Mass or Volume Output= 0
Output Increment Type= 1
Profile and TS Output Increment= 1
Transport Output Increment 1
XS Output Flag= 0
XS Output Increment= 10
Read HDF5 Sediment Hotstart= 0
Sediment Hotstart Type= 0
Write Gradation File= 0
Read Gradation Hotstart= 0
Write HDF5 File= 1
Write Binary Output= 1
Write DSS Sediment File= 0
DSS Sediment Output Type= 1
SV Curve= 0
Specific Gage Flag= 0
Subcell Erosion Methods= 0
Subcell Deposition Methods= 0
Advection Scheme= 1
Matrix Solver= 0
Implicit Weighting Factor= 1
Maximum Outer Loop Convergence Iterations= 5
Convergence Maximum Absolute= 0.001
Convergence RMSE= 0.0001
Grain Fractions Max Abs Error= 0.001
Max Subgrid Regions= 1
Max Subgrid Length Scale= 3.402823E+38
Initial Layer Thickness= 3.402823E+38
Min Layer Thickness= 3.402823E+38
Max Layer Thickness= 3.402823E+38
Number of Layers= 5

--- WANLESSRN.f01 (steady flow) ---

Flow Title=Flow
Program Version=6.10
Number of Profiles= 6
Profile Names=01pct,10pct,04pct,02pct,0_2pct,01plus
River Rch & RM=WANLESSRN,Main            ,4318
     655     348     462     555     913     969
Boundary for River Rch & Prof#=WANLESSRN,Main            , 1
Up Type= 0
Dn Type= 3
Dn Slope=0.03477
Boundary for River Rch & Prof#=WANLESSRN,Main            , 2
Up Type= 0
Dn Type= 3
Dn Slope=0.03477
Boundary for River Rch & Prof#=WANLESSRN,Main            , 3
Up Type= 0
Dn Type= 3
Dn Slope=0.03477
Boundary for River Rch & Prof#=WANLESSRN,Main            , 4
Up Type= 0
Dn Type= 3
Dn Slope=0.03477
Boundary for River Rch & Prof#=WANLESSRN,Main            , 5
Up Type= 0
Dn Type= 3
Dn Slope=0.03477
Boundary for River Rch & Prof#=WANLESSRN,Main            , 6
Up Type= 0
Dn Type= 3
Dn Slope=0.03477
DSS Import GetInterval= 0
DSS Import GetPeak= 0
DSS Import FillOption= 0

--- WANLESSRN.g01 (geometry) ---

Geom Title=Geometry
Program Version=6.10

River Reach=WANLESSRN       ,Main
Reach XY= 30
     2285400.879      526651.192     2285480.484      526639.905
     2285555.181      526578.163     2285632.514       526578.59
     2285668.361       526559.13     2285744.404      526366.292
     2285834.537      526265.7392286020.00161114526197.579980378
     2286354.958      526126.483     2286525.252      526176.211
     2286834.036      526179.283     2287151.896      526077.111
     2287277.468      526012.053     2287431.355      526003.237
     2287542.062       526084.07     2287585.404      526157.372
     2287651.392      526218.412     2287714.656      526237.556
     2287844.673      526218.173     2287980.822      526105.977
     2288151.026      526037.959     2288199.436      525944.246
     2288308.883      525818.934     2288510.308      525708.877
     2288548.958      525587.483     2288616.971      525502.303
     2288656.193       525404.51     2288697.861      525361.255
     2288763.974      525332.836     2288847.751       525225.54

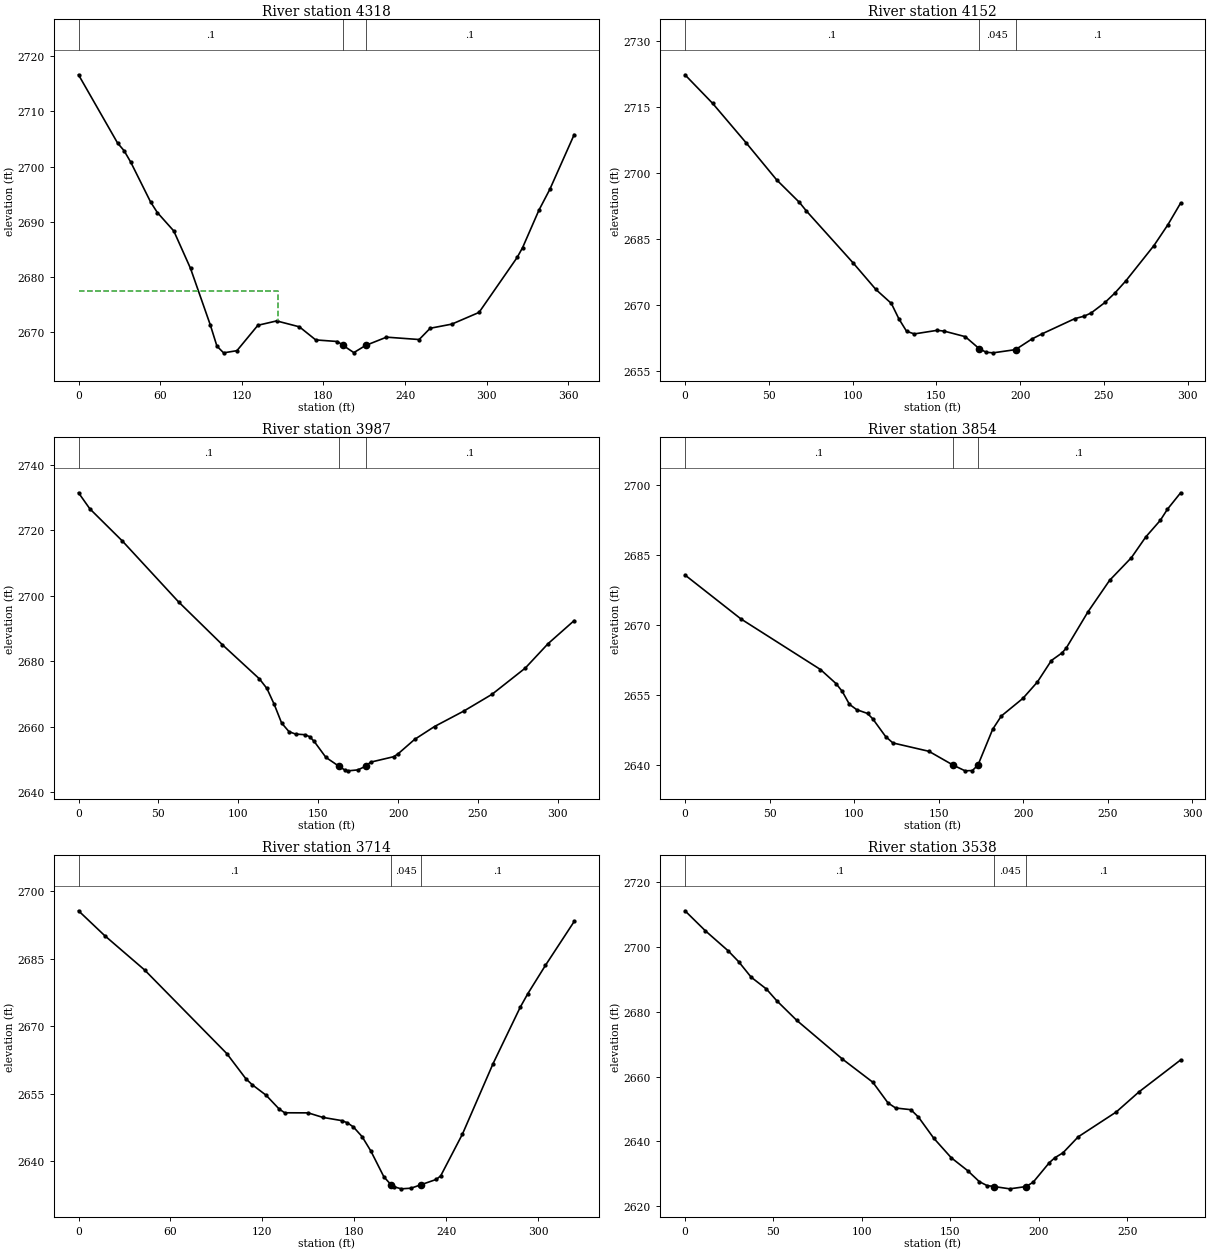
Type RM Length L Ch R = 1 ,4318    ,166.1,166.1,166.1
XS GIS Cut Line= 3
 2285492.1093869526828.7148081562285406.87577639526706.118519069
 2285409.2109438526491.283117239
#Sta/Elev= 30
       0 2716.64    28.7 2704.28    33.5 2702.89    38.4 2700.81      53 2693.59
    57.9  2691.7      70 2688.36    82.3 2681.58    96.9  2671.3   101.7 2667.51
   106.6 2666.29   116.4 2666.68   131.8 2671.28   145.6 2672.07   162.3    2671
   174.3 2668.63   190.3 2668.34   194.3 2667.65   202.3 2666.33   210.9 2667.62
   226.3 2669.13   250.3  2668.7   258.4 2670.74   274.3 2671.49   294.3 2673.61
   322.3 2683.56   326.3 2685.34   338.3 2692.12   346.3 2695.89   364.2  2705.8
#Mann= 3 ,-1,0
       0      .1       0   194.3    .045       0   210.9      .1       0
#XS Ineff= 2 , 0
          146.48 2677.42
Permanent Ineff=
       F       F
Bank Sta=194.3,210.9
XS Rating Curve= 0 ,0
Exp/Cntr(USF)=0,0
Exp/Cntr=0.3,0.1

Type RM Length L Ch R = 1 ,4152    ,164.9,164.9,164.9
XS GIS Cut Line= 3
2285630.64990968526749.0483847632285558.05119299526616.881490269
2285517.09807075526477.889075401
#Sta/Elev= 30
       0 2722.41    16.5 2715.91    36.4 2706.98    54.7 2698.52    68.3 2693.39
    72.4 2691.46   100.3 2679.65   113.9  2673.6   123.1 2670.44   127.6 2666.94
   132.2  2664.1   136.8  2663.5   150.5 2664.32   154.7 2664.13   167.2 2662.88
   175.5 2660.16   179.7 2659.33   183.8  2659.2   197.2 2659.93   206.8 2662.31
     213 2663.51   232.6 2666.98   238.1 2667.53   242.3 2668.26   250.6 2670.66
   256.5  2672.8   263.1  2675.6   279.8  2683.6   288.1 2688.32   295.7 2693.25
#Mann= 3 ,-1,0
       0      .1       0   175.5    .045       0   197.2      .1       0
Bank Sta=175.5,197.2
XS Rating Curve= 0 ,0
Exp/Cntr(USF)=0,0
Exp/Cntr=0.3,0.1

Type RM Length L Ch R = 1 ,3987    ,132.4,132.4,132.4
XS GIS Cut Line= 2
2285834.21141264526612.7118226212285565.66716035526457.423189777
#Sta/Elev= 30
       0  2731.4     7.1  2726.5    27.5 2716.65    62.6  2698.1    90.1 2684.98
   113.2  2674.6   117.9 2671.67   122.5 2666.78   127.1 2661.12   131.7 2658.49
   135.8 2657.74   141.7 2657.54   144.6 2656.96   147.5 2655.49   154.8 2650.63
  162.872647.948   166.9 2646.69   168.7 2646.51   174.9  2646.8   179.7 2647.93
   182.8 2649.16   197.3 2650.83   200.2 2651.79   210.3 2656.09   222.8 2660.04
   241.2 2664.78   258.8 2669.88   279.6 2677.88   293.9 2685.35   310.2 2692.38
#Mann= 3 ,-1,0
       0      .1       0  162.87    .045       0   179.7      .1       0
Bank Sta=162.87,179.7
XS Rating Curve= 0 ,0
Exp/Cntr(USF)=0,0
Exp/Cntr=0.3,0.1

Type RM Length L Ch R = 1 ,3854    ,140.4,140.4,140.4
XS GIS Cut Line= 2
2285883.19416348526461.1355253952285608.93234486526358.132217949
#Sta/Elev= 30
       0 2680.67    33.1 2671.26    80.1 2660.44    89.3 2657.43      93 2655.74
    97.2    2653   101.5 2651.85   107.9 2651.04     111 2649.89   118.6  2646.1
   122.9 2644.73   144.2 2642.94  158.462639.993   165.6 2638.76   169.9 2638.83
   173.2 2639.99   181.9 2647.66     187 2650.49   199.8 2654.28   208.3 2657.76
   216.6 2662.37   222.9    2664   225.4 2665.04   238.2 2672.77     251 2679.52
   263.9 2684.38   272.4 2688.81     281 2692.37   285.2 2694.74     293 2698.26
#Mann= 3 ,-1,0
       0      .1       0  158.46    .045       0   173.2      .1       0
Bank Sta=158.46,173.2
XS Rating Curve= 0 ,0
Exp/Cntr(USF)=0,0
Exp/Cntr=0.3,0.1

Type RM Length L Ch R = 1 ,3714    ,175.9,175.9,175.9
XS GIS Cut Line= 2
2285938.12636243526455.0880223662285738.46954878526200.554774547
#Sta/Elev= 30
       0 2695.64      17 2690.15    43.1 2682.51    96.8 2663.92   109.2 2658.35
   113.3 2657.03   122.4 2654.69     131  2651.6   134.6 2650.78   149.9 2650.76
   159.4 2649.76   171.7 2649.05   175.3 2648.59   179.4 2647.64   185.1 2645.48
   190.8 2642.29   199.3 2636.56   204.1 2634.75   205.8 2634.37   210.6 2633.89
     217 2634.03   223.5  2634.8   233.5 2635.98   236.4 2636.78   250.6 2646.06
   270.6 2661.72   288.3 2674.22   293.3 2677.26   304.7 2683.49   323.5 2693.26
#Mann= 3 ,-1,0
       0      .1       0   204.1    .045       0   223.5      .1       0
Bank Sta=204.1,223.5
XS Rating Curve= 0 ,0
Exp/Cntr(USF)=0,0
Exp/Cntr=0.3,0.1

Type RM Length L Ch R = 1 ,3538    ,129.5,129.5,129.5
XS GIS Cut Line= 2
2286032.73510983526387.9163068492285929.73180239526127.305528973
#Sta/Elev= 30
       0 2711.11    11.5 2704.95    24.4 2698.77    30.3 2695.44    37.4 2690.64
      46    2687    51.9 2683.36    63.2 2677.31      89 2665.38   106.2 2658.23
   114.8 2651.83   119.1 2650.29   127.7 2649.77     132 2647.48   140.6    2641
   150.5 2634.96   159.8 2630.97   166.4 2627.58   170.7 2626.38   174.6 2626.08
   183.6 2625.36  192.78 2626.06   196.8 2627.38     206 2633.45   209.1 2634.95
   213.7 2636.47   222.3  2641.4   243.8 2649.06   256.7 2655.28   280.2 2665.11
#Mann= 3 ,-1,0
       0      .1       0   174.6    .045       0  192.78      .1       0
Bank Sta=174.6,192.78
XS Rating Curve= 0 ,0
Exp/Cntr(USF)=0,0
Exp/Cntr=0.3,0.1

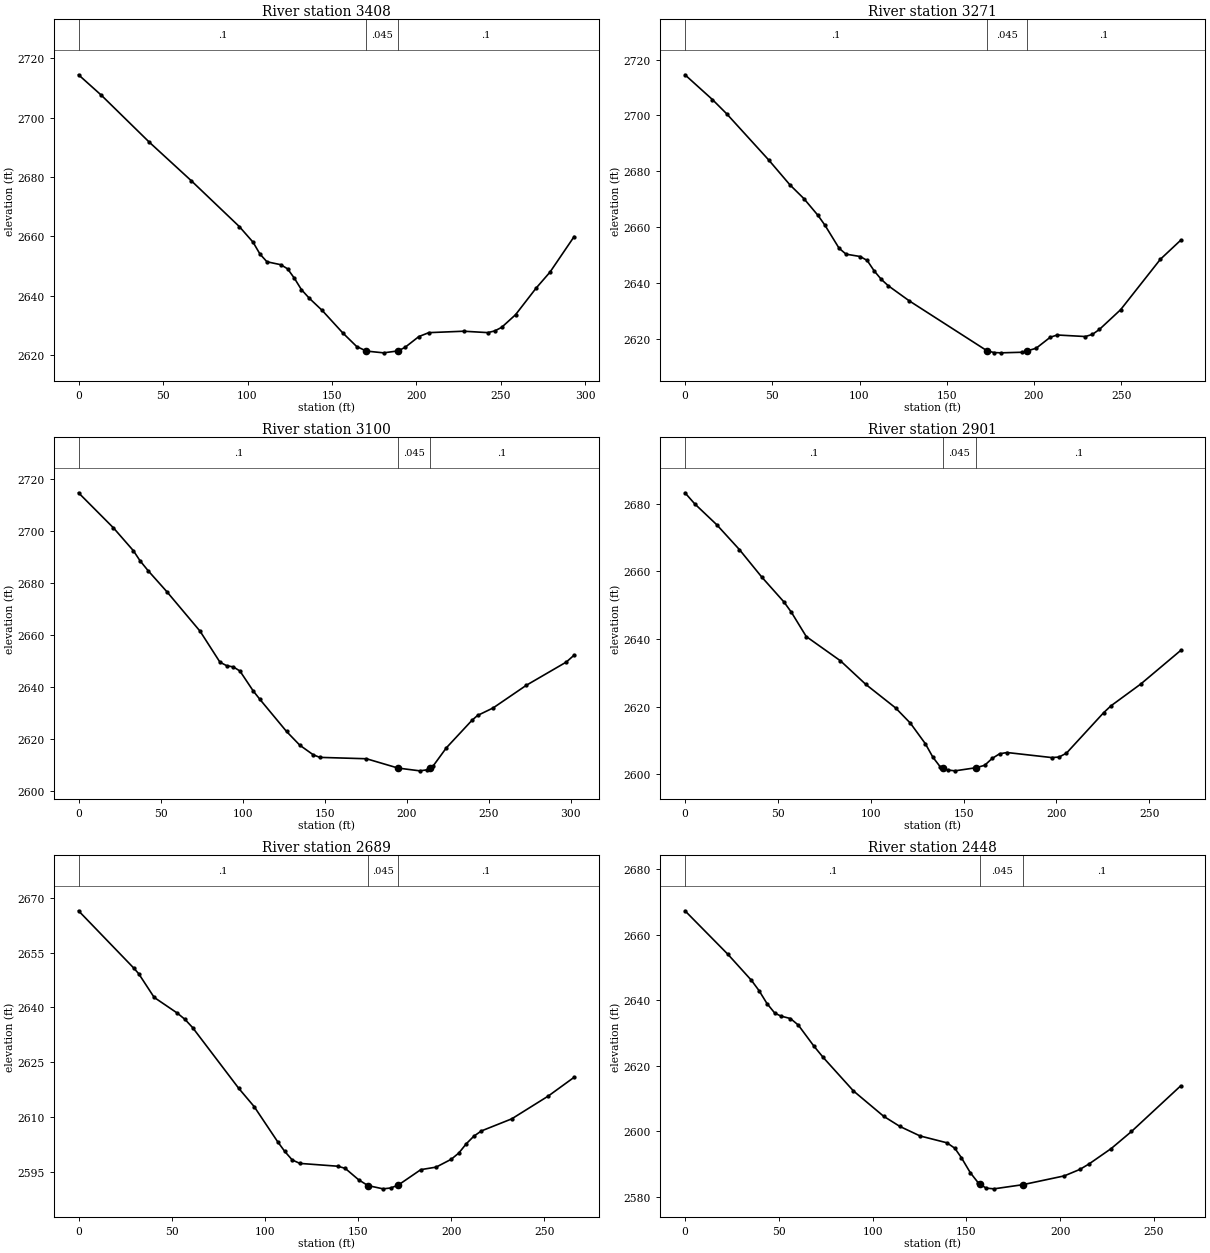
Type RM Length L Ch R = 1 ,3408    ,137.4,137.4,137.4
XS GIS Cut Line= 2
2286128.44250644526366.3516607412286068.89573746526079.126069165
#Sta/Elev= 30
       0 2714.45    13.5 2707.56      42 2691.66    66.6 2678.79    95.2 2663.24
   103.3 2657.98   107.4 2653.97   111.5 2651.39   119.7  2650.4   123.7 2649.02
   127.8 2645.79   131.9    2642   136.6 2639.07   144.2 2634.98   156.4 2627.38
   164.6 2622.81   170.4 2621.27   180.5 2620.68   189.1 2621.33   193.2 2622.52
   201.4 2626.17   207.3 2627.49   227.9 2627.97   242.2  2627.5   246.3 2628.07
   250.4 2629.28   258.6 2633.53   270.8 2642.52     279  2647.9   293.3  2659.9
#Mann= 3 ,-1,0
       0      .1       0   170.4    .045       0   189.1      .1       0
Bank Sta=170.4,189.1
XS Rating Curve= 0 ,0
Exp/Cntr(USF)=0,0
Exp/Cntr=0.3,0.1

Type RM Length L Ch R = 1 ,3271    ,171.1,171.1,171.1
XS GIS Cut Line= 2
2286248.04925251 526340.758166092286212.06014509526059.050325244
#Sta/Elev= 30
       0 2714.56    15.7  2705.7    23.8 2700.65      48 2684.03    60.1 2675.16
    68.1 2670.23    76.2 2664.21    80.2 2660.68    88.3 2652.43    92.3 2650.31
   100.4 2649.47   104.4 2648.06   108.5 2644.24   112.5 2641.28   116.5 2638.99
   128.6 2633.55     173 2615.73     177 2615.08     181 2614.97   193.1 2615.18
   196.12615.678   201.2 2616.61   209.3 2620.56   213.3 2621.36   229.4 2620.81
   233.5 2621.59   237.5 2623.38   249.6 2630.41   272.4 2648.49     284 2655.28
#Mann= 3 ,-1,0
       0      .1       0     173    .045       0   196.1      .1       0
Bank Sta=173,196.1
XS Rating Curve= 0 ,0
Exp/Cntr(USF)=0,0
Exp/Cntr=0.3,0.1

Type RM Length L Ch R = 1 ,3100    ,198.6,198.6,198.6
XS GIS Cut Line= 2
2286356.12132904526330.1565658682286407.49501208526032.422720941
#Sta/Elev= 30
       0 2714.88    21.3 2701.35    33.5 2692.51    37.5 2688.68    42.4 2684.87
    53.8 2676.79    74.1 2661.52    86.2 2649.59    90.3 2648.23    94.4 2647.75
    98.4 2646.17   106.5 2638.48   110.6 2635.22   126.8 2622.87   134.9 2617.57
   143.1 2613.87   147.1 2612.89   175.5 2612.36   194.8 2608.76     208  2607.7
   212.1 2608.06  214.06 2608.78   216.1 2609.54   224.2 2616.57   239.8 2627.17
   243.2 2629.04   252.7 2631.94     273  2640.7   297.3 2649.63   302.1 2652.31
#Mann= 3 ,-1,0
       0      .1       0   194.8    .045       0  214.06      .1       0
Bank Sta=194.8,214.06
XS Rating Curve= 0 ,0
Exp/Cntr(USF)=0,0
Exp/Cntr=0.3,0.1

Type RM Length L Ch R = 1 ,2901    ,211.7,211.7,211.7
XS GIS Cut Line= 2
2286584.36125634526326.4866234922286576.29473226526059.670827096
#Sta/Elev= 30
       0 2683.23     5.3 2679.93      17 2673.84    29.3 2666.44    41.3 2658.34
    53.3 2650.94    57.3  2647.9    65.3 2640.72    83.7 2633.55    97.4 2626.55
   113.4 2619.61   121.4 2615.08   129.4 2609.05   133.5 2605.03   137.4 2602.22
   138.8 2601.88   141.4 2601.25   145.4    2601   156.8 2601.93   161.4 2602.64
   165.4 2604.67   169.4 2606.03   173.4 2606.42   197.4 2604.93   201.4 2605.07
   205.4 2606.22   225.4 2618.17   229.4 2620.23   245.4 2626.66   266.9 2636.59
#Mann= 3 ,-1,0
       0      .1       0   138.8    .045       0   156.8      .1       0
Bank Sta=138.8,156.8
XS Rating Curve= 0 ,0
Exp/Cntr(USF)=0,0
Exp/Cntr=0.3,0.1

Type RM Length L Ch R = 1 ,2689    ,240.9,240.9,240.9
XS GIS Cut Line= 3
2286800.97072087526332.4917332792286775.28387934526232.079534598
2286803.30588828526072.120566932
#Sta/Elev= 30
       0 2666.45    29.7 2650.75    32.3 2649.23    40.6 2642.75      53 2638.46
    57.1 2636.75    61.2 2634.51      86 2617.86    94.3 2612.85   106.9 2603.24
   110.7  2600.6   114.7 2598.27   118.8 2597.33   139.1 2596.56   143.1 2595.98
   150.4 2592.82   155.3 2591.27   163.4 2590.37   167.5  2590.6   171.6  2591.4
   183.7 2595.62   191.9 2596.31     200 2598.45   204.1 2600.17   208.1  2602.7
   212.2 2604.79   216.2 2606.21   232.5 2609.52   252.1 2615.76     266  2620.9
#Mann= 3 ,-1,0
       0      .1       0   155.3    .045       0   171.6      .1       0
Bank Sta=155.3,171.6
XS Rating Curve= 0 ,0
Exp/Cntr(USF)=0,0
Exp/Cntr=0.3,0.1

Type RM Length L Ch R = 1 ,2448    ,151.6,151.6,151.6
XS GIS Cut Line= 2
 2287057.8391361526267.1070457662286983.11377894526013.741381652
#Sta/Elev= 30
       0 2667.32    22.9 2654.01    35.4 2646.09    39.5 2642.91    43.7 2638.99
    47.9 2636.04    51.2 2635.14    56.2  2634.4    60.4 2632.41    68.7 2625.99
    73.7  2622.5    89.8 2612.28   105.9 2604.54   114.6 2601.42   125.3 2598.53
   139.6 2596.44   143.8 2594.79   147.3 2591.93   152.1 2587.29   156.3 2584.23
   157.5 2583.72   160.5 2582.59   164.7 2582.37     180 2583.63   202.2 2586.33
   210.5 2588.31   215.4 2589.98   227.2 2594.68     238 2599.89   264.2 2613.82
#Mann= 3 ,-1,0
       0      .1       0   157.5    .045       0     180      .1       0
Bank Sta=157.5,180
XS Rating Curve= 0 ,0
Exp/Cntr(USF)=0,0
Exp/Cntr=0.3,0.1

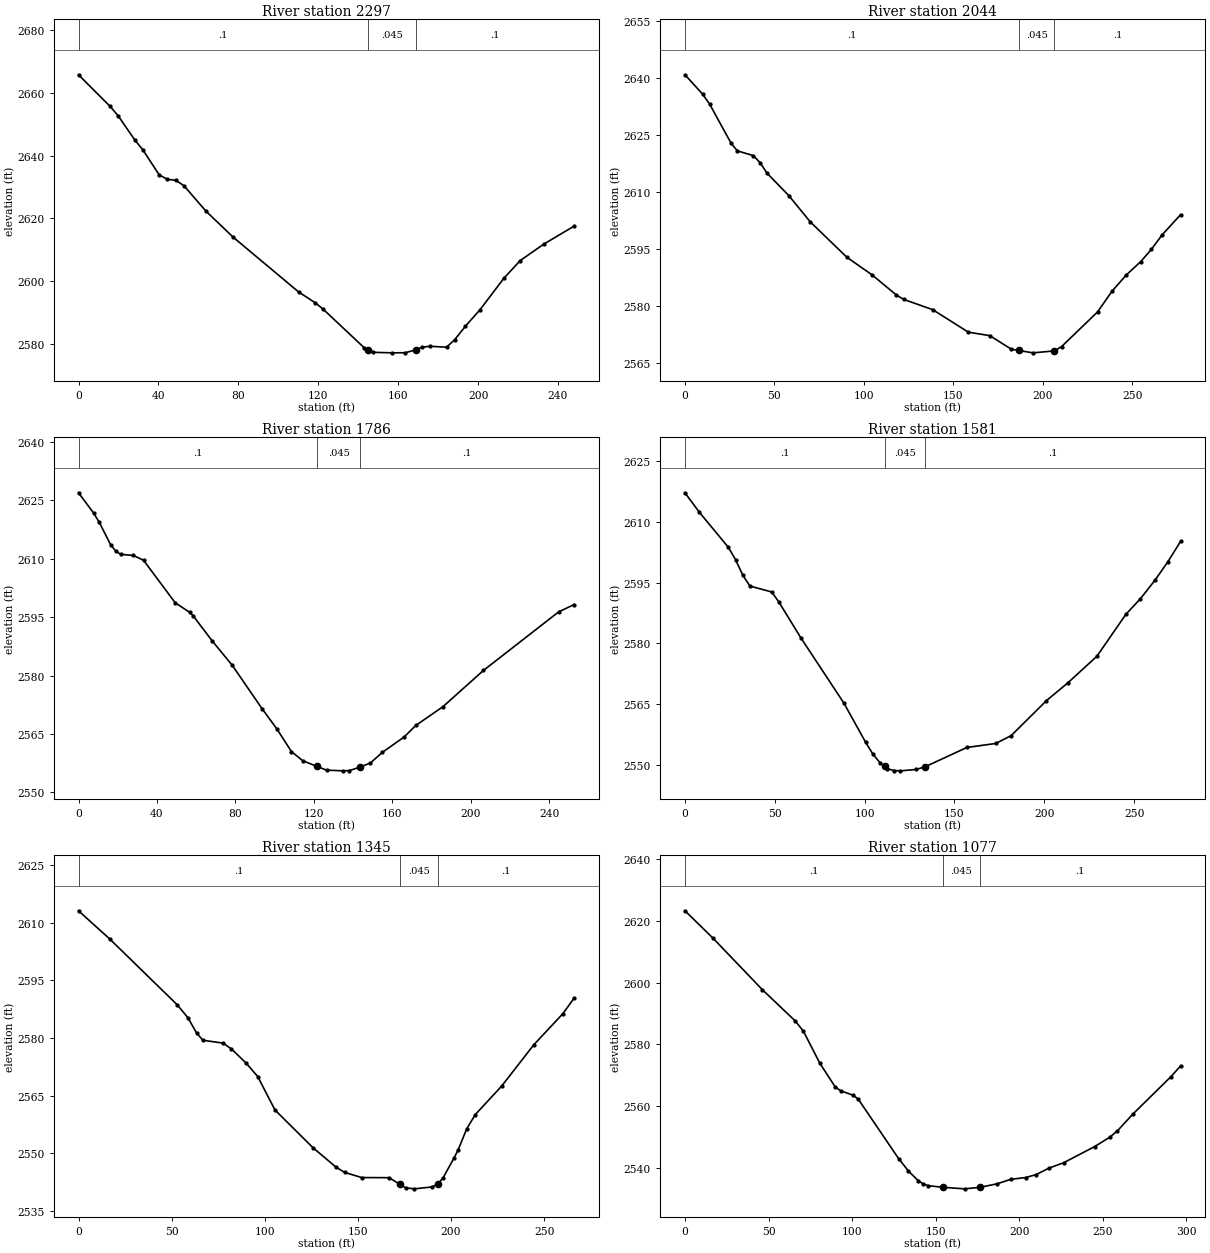
Type RM Length L Ch R = 1 ,2297    ,253.2,253.2,253.2
XS GIS Cut Line= 2
2287193.27884595526228.5767834812287137.23482808525986.886956423
#Sta/Elev= 30
       0  2665.7    15.8 2655.67    19.9 2652.61    28.1 2645.03    32.2 2641.83
    40.4 2633.85    44.5 2632.45    48.7 2632.14    52.8 2630.41    63.7 2622.39
    77.4 2614.06   110.2 2596.62   118.5 2593.19   122.6 2591.07   143.1 2578.82
   144.92578.214   147.2 2577.44   157.1 2577.27   163.6 2577.31   168.8 2578.23
   171.8 2579.05   175.9 2579.36   184.2 2579.06   188.3 2581.45   193.7 2585.77
   200.9 2590.92   212.9 2600.98   221.1 2606.62   232.9 2611.85   248.1 2617.58
#Mann= 3 ,-1,0
       0      .1       0   144.9    .045       0   168.8      .1       0
Bank Sta=144.9,168.8
XS Rating Curve= 0 ,0
Exp/Cntr(USF)=0,0
Exp/Cntr=0.3,0.1

Type RM Length L Ch R = 1 ,2044    ,258.1,258.1,258.1
XS GIS Cut Line= 2
2287407.02722034 526198.946670852287384.99456671525922.923254475
#Sta/Elev= 30
       0  2640.9     9.8 2635.83    13.8 2633.14    25.8 2622.81    29.3 2620.83
    38.1 2619.61    41.9 2617.77    45.9 2614.93      58 2609.04      70 2602.12
    90.4  2592.8   104.6 2588.12   118.1 2582.83   122.2 2581.68   138.4 2578.97
   158.3 2573.04   170.3 2572.12   182.3 2568.56   186.4 2568.22   186.4 2568.21
   194.4 2567.59   206.4  2568.1   210.4 2569.24   230.5 2578.38   238.5 2583.79
   246.5  2588.1   254.6 2591.63   260.5 2594.84   266.6 2598.71   276.9 2604.03
#Mann= 3 ,-1,0
       0      .1       0   186.4    .045       0   206.4      .1       0
Bank Sta=186.4,206.4
XS Rating Curve= 0 ,0
Exp/Cntr(USF)=0,0
Exp/Cntr=0.3,0.1

Type RM Length L Ch R = 1 ,1786    ,204.8,204.8,204.8
XS GIS Cut Line= 3
2287484.70570727526244.5935940072287660.93196971526074.562871546
2287658.07658637526067.182557706
#Sta/Elev= 30
       0 2626.97     7.7 2621.77    10.5 2619.46    16.4 2613.61      19    2612
    21.5 2611.15      28 2610.87    33.2 2609.62    49.3 2598.72    56.8 2596.23
    58.6 2595.28    68.3 2588.84    78.4 2582.66    93.8 2571.37   101.1 2566.36
   108.6 2560.49   114.4 2558.12   121.5 2556.71   126.5 2555.72     135 2555.54
   138.2 2555.61   143.8 2556.54   148.9 2557.57   154.9 2560.26   166.1 2564.25
     172 2567.19   185.9 2572.03   206.5 2581.32   244.9 2596.38   252.8 2598.26
#Mann= 3 ,-1,0
       0      .1       0   121.5    .045       0   143.8      .1       0
Bank Sta=121.5,143.8
XS Rating Curve= 0 ,0
Exp/Cntr(USF)=0,0
Exp/Cntr=0.3,0.1

Type RM Length L Ch R = 1 ,1581    ,236.3,236.3,236.3
XS GIS Cut Line= 2
2287768.27879012526353.1682031322287738.49470122 526078.90638451
#Sta/Elev= 30
       0 2617.25       8 2612.43    24.1 2603.79    28.2 2600.67    32.2 2596.85
    36.2 2594.17    48.3 2592.72    52.3 2590.21    64.4 2581.45    88.5  2565.2
   100.6 2555.51   104.6 2552.62   108.6 2550.47   111.12549.588   112.6 2549.03
   116.2 2548.56   119.9 2548.48   128.7 2548.82   133.7 2549.49   156.9 2554.26
     173 2555.25   181.6  2557.2   201.2 2565.84   213.2 2570.27   229.3 2576.82
   245.4 2587.18   253.5 2591.04   261.7 2595.68   268.7 2600.12   275.9 2605.25
#Mann= 3 ,-1,0
       0      .1       0   111.1    .045       0   133.7      .1       0
Bank Sta=111.1,133.7
XS Rating Curve= 0 ,0
Exp/Cntr(USF)=0,0
Exp/Cntr=0.3,0.1

Type RM Length L Ch R = 1 ,1345    ,267.5,267.5,267.5
XS GIS Cut Line= 2
2288046.78253473526283.4532176442287909.00765747526055.774395053
#Sta/Elev= 30
       0 2613.05    16.7 2605.75    53.1 2588.56    58.8  2585.2    63.4 2581.26
    66.8 2579.39    77.5 2578.66    82.1 2577.14      90 2573.45    96.2 2569.97
   105.5 2561.25   125.9 2551.45   138.2 2546.43   142.9 2545.03   152.1  2543.7
   166.7 2543.67   172.5 2541.96   175.6 2541.04   180.3 2540.77   189.7 2541.26
   192.9 2541.98   195.8  2543.7   201.6 2548.79   203.7 2550.79   208.4 2556.35
     213 2560.07   227.1 2567.44   244.5 2578.26   259.9 2586.23   266.1 2590.35
#Mann= 3 ,-1,0
       0      .1       0   172.5    .045       0   192.9      .1       0
Bank Sta=172.5,192.9
XS Rating Curve= 0 ,0
Exp/Cntr(USF)=0,0
Exp/Cntr=0.3,0.1

Type RM Length L Ch R = 1 ,1077    ,240.8,240.8,240.8
XS GIS Cut Line= 3
2288288.47236179526118.8239151552288220.75250687526024.249635002
2288063.12870661525936.680857083
#Sta/Elev= 30
       0 2623.28    16.8 2614.39    46.3 2597.73      66 2587.59    70.9 2584.26
    80.7  2573.9    89.8 2566.32    93.1 2564.99   100.4  2563.6   103.6 2562.35
   127.8 2543.05   133.7 2539.01   139.6 2535.87   142.5 2534.84   145.5 2534.26
   154.3 2533.73   167.3 2533.23   176.5 2533.72   186.7 2534.85   194.8 2536.29
   203.9  2536.9   210.2 2537.85   217.6 2539.88   226.8 2541.74   245.1  2546.9
   254.3 2549.98   258.8 2552.02     268 2557.43   290.9 2569.61   296.6 2573.06
#Mann= 3 ,-1,0
       0      .1       0   154.3    .045       0   176.5      .1       0
Bank Sta=154.3,176.5
XS Rating Curve= 0 ,0
Exp/Cntr(USF)=0,0
Exp/Cntr=0.3,0.1

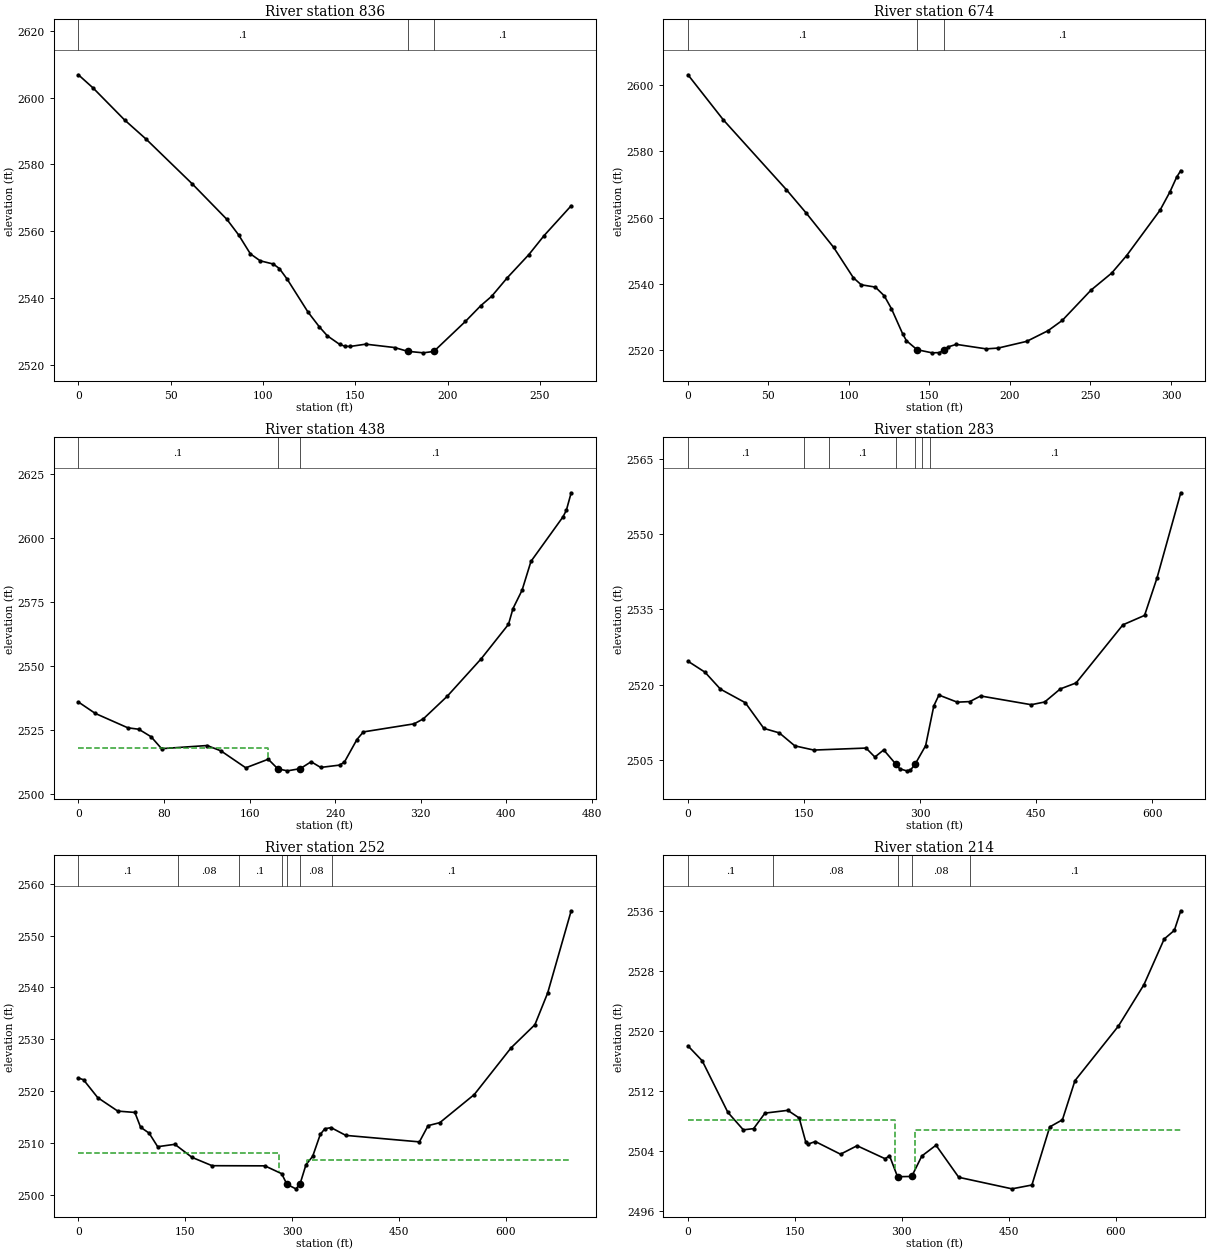
Type RM Length L Ch R = 1 ,836     ,162.7,162.7,162.7
XS GIS Cut Line= 2
 2288435.5879087525953.0270289612288265.12068768525747.532296777
#Sta/Elev= 30
       0 2606.88       8 2602.91      25 2593.36    36.7 2587.59    61.7 2574.18
    80.5 2563.52    86.8  2558.9    93.2  2553.2    98.5 2551.12   105.6 2550.15
   108.9  2548.8   113.1 2545.64   124.4 2535.76   130.6 2531.29   134.9 2528.63
   141.5 2526.09   144.3 2525.52   147.2 2525.44   155.7 2526.13   171.3 2525.12
   178.4 2523.99   186.9 2523.53   192.6 2523.96   209.7 2532.95   218.1 2537.71
   223.9 2540.47   232.4 2546.05   244.1    2553   252.3 2558.66     267 2567.62
#Mann= 3 ,-1,0
       0      .1       0   178.4    .045       0   192.6      .1       0
Bank Sta=178.4,192.6
XS Rating Curve= 0 ,0
Exp/Cntr(USF)=0,0
Exp/Cntr=0.3,0.1

Type RM Length L Ch R = 1 ,674     ,235.5,235.5,235.5
XS GIS Cut Line= 3
2288554.45463671 525861.730736282288448.96932186525723.358823265
2288329.83296625525666.272652873
#Sta/Elev= 30
       0 2603.08      22 2589.47    61.1 2568.46    73.4 2561.42    90.5 2551.04
   102.7 2541.91   107.6 2539.77   116.4 2539.07   121.9 2536.45   126.4 2532.55
   133.3 2525.04   135.7  2522.9   142.3  2520.2   151.6 2519.25   156.1 2519.32
     159 2520.05   161.8 2521.08   166.7  2521.8   185.2 2520.45   192.6 2520.68
   210.4 2522.71   223.7 2525.94   232.5 2529.03   250.3 2538.14   263.2  2543.3
   272.5 2548.59   293.2 2562.24   299.4  2567.8   303.5 2572.18   306.1  2574.2
#Mann= 3 ,-1,0
       0      .1       0   142.3    .045       0     159      .1       0
Bank Sta=142.3,159
XS Rating Curve= 0 ,0
Exp/Cntr(USF)=0,0
Exp/Cntr=0.3,0.1

Type RM Length L Ch R = 1 ,438     ,154.8,154.8,154.8
XS GIS Cut Line= 4
2288695.95907504525699.661364847 2288645.7529757525582.902994288
2288497.46984509525511.6803882472288336.34329372525563.054071293
#Sta/Elev= 30
       0 2536.01    15.8 2531.55    46.2 2525.94    56.5 2525.37      68 2522.44
    77.8 2517.79   120.3 2519.02   133.3 2516.93   156.5 2510.32   177.5 2513.67
   186.5 2509.91   195.5 2509.14   207.5 2510.01   217.6 2512.69   226.5 2510.47
   244.2 2511.38   248.7 2512.55   260.4 2521.35   266.4 2524.33   313.9 2527.49
   322.5 2529.43   344.8 2538.24   376.6 2552.89   402.1 2566.33   406.3 2572.47
   414.8 2579.64   423.1 2590.88     453 2608.24   456.2 2610.84   460.7 2617.66
#Mann= 3 ,-1,0
       0      .1       0   186.5    .045       0   207.5      .1       0
#XS Ineff= 2 , 0
          177.18 2517.95
Permanent Ineff=
       F       F
Bank Sta=186.5,207.5
XS Rating Curve= 0 ,0
Exp/Cntr(USF)=0,0
Exp/Cntr=0.3,0.1

Type RM Length L Ch R = 1 ,283     ,31,31,31
BEGIN DESCRIPTION:
structure xs 4
END DESCRIPTION:
XS GIS Cut Line= 4
 2288738.3178443525651.1996355632288743.42485543 525488.62644798
 2288515.3116917525314.1369010982288329.75695404525338.820788217
#Sta/Elev= 30
       0 2524.69      22  2522.5      42 2519.12    74.1 2516.42    98.1  2511.3
   118.1  2510.4   138.1 2507.82   162.7 2506.98   230.2 2507.38   241.6 2505.59
     253 2507.01   268.7 2504.18   273.7 2503.25   282.6 2502.84   287.6 2502.99
   293.4 2504.11   307.2 2507.85   317.8  2515.8   324.4 2517.94     348 2516.53
   364.3 2516.64   378.3 2517.76   443.7 2516.02   461.1 2516.56   481.3 2519.17
   501.7 2520.36   562.2 2531.94   590.2 2533.82   606.4 2541.34     637 2558.26
#Mann= 7 ,-1,0
       0      .1       0     150     .08       0  182.65      .1       0
   268.7    .045       0   293.4      .1       0  302.65     .08       0
  312.65      .1       0
Bank Sta=268.7,293.4
XS Rating Curve= 0 ,0
Exp/Cntr(USF)=0,0
Exp/Cntr=0.5,0.3

Type RM Length L Ch R = 1 ,252     ,38.7,38.7,38.7
BEGIN DESCRIPTION:
structure xs 3; 10.1 ft between structure and xs
END DESCRIPTION:
XS GIS Cut Line= 4
2288767.25757403525644.3902873922288774.91809072525479.263594245
2288530.63272508525280.0901602432288321.24526882525307.327552926
#Sta/Elev= 30
       0 2522.56     7.2 2522.22    27.2 2518.77    55.3 2516.18    79.3 2515.92
    87.3 2513.08    99.3 2511.93   111.3 2509.32   135.4 2509.78   159.4 2507.27
   187.6 2505.66   261.7 2505.63   285.3 2504.12   292.7 2502.07   305.2  2501.2
   310.9 2502.06   319.4 2505.84   328.8 2507.46   339.5 2511.69   345.8 2512.77
   354.6    2513   375.3  2511.5   478.6 2510.25   490.8 2513.38   507.2 2513.95
   555.6 2519.37   607.3 2528.38   640.7 2532.83   658.6 2538.94   691.6 2554.78
#Mann= 7 ,-1,0
       0      .1       0     140     .08       0   225.3      .1       0
   285.3     .08       0   292.7    .045       0   310.9     .08       0
   355.3      .1       0
#XS Ineff= 2 , 0
             281  2508.2     321          2506.8
Permanent Ineff=
       F       F
Bank Sta=292.7,310.9
XS Rating Curve= 0 ,0
Exp/Cntr(USF)=0,0
Exp/Cntr=0.5,0.3

Type RM Length L Ch R = 1 ,214     ,76.8,76.8,76.8
BEGIN DESCRIPTION:
structure xs 2; 14.3 ft between structure and xs
END DESCRIPTION:
XS GIS Cut Line= 4
2288794.92055097525617.1528947082288802.58106766525452.026201561
2288558.29570203525252.8527675582288348.90824577525280.090160242
#Sta/Elev= 30
       0 2518.06      20 2516.07      56 2509.19    77.7 2506.86    92.1 2507.02
   108.1 2509.09   140.1 2509.46   156.1 2508.44   165.3 2505.24   168.4 2504.95
   178.7  2505.3   214.1 2503.61   237.3 2504.74   276.8    2503   282.8 2503.42
   294.1 2500.61     314 2500.64   328.2 2503.37   348.1 2504.81     380 2500.53
   454.7 2498.99   482.7  2499.5   507.7 2507.25   525.5  2508.2   543.1 2513.42
     604 2520.69   639.9 2526.22   668.3 2532.31   682.6 2533.47   691.6 2536.08
#Mann= 5 ,-1,0
       0      .1       0     120     .08       0   294.1    .045       0
     314     .08       0   395.3      .1       0
#XS Ineff= 2 , 0
             290  2508.2   318.5          2506.8
Permanent Ineff=
       F       F
Bank Sta=294.1,314
XS Rating Curve= 0 ,0
Exp/Cntr(USF)=0,0
Exp/Cntr=0.5,0.3

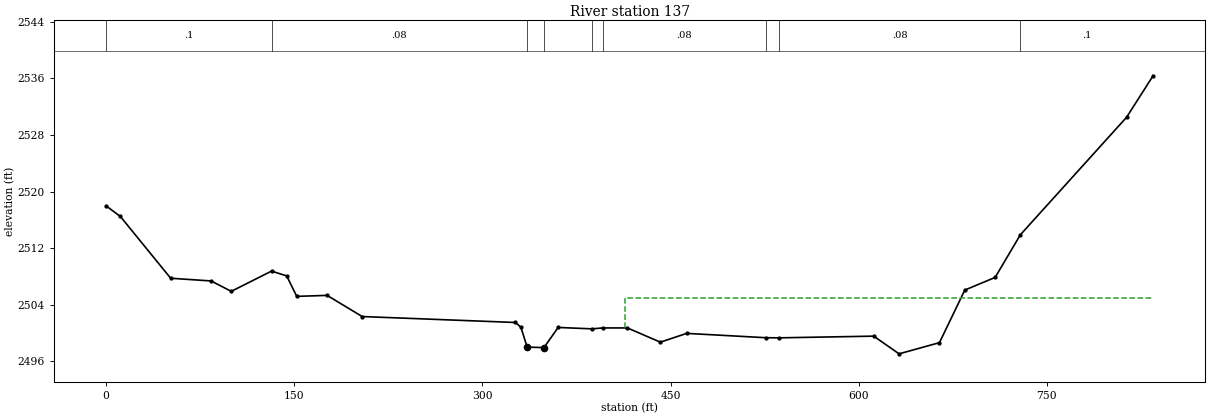
Type RM Length L Ch R = 1 ,137     ,,,
BEGIN DESCRIPTION:
structure xs 1
END DESCRIPTION:
XS GIS Cut Line= 4
2288831.94638165525632.4739280932288854.07676321525409.467775492
2288592.76802714525187.3127914122288327.20344847525220.508363746
#Sta/Elev= 30
       0 2517.98    11.4 2516.48    51.5 2507.75    83.7 2507.37    99.8  2505.9
   131.9 2508.76     144 2508.08     152 2505.19   176.2 2505.33   204.2 2502.34
   326.4  2501.5   330.7 2500.83   335.7 2498.02  349.112497.949   360.4  2500.8
   387.4  2500.6   395.9 2500.73   415.6 2500.73   441.9 2498.72   462.9 2499.96
   525.9 2499.35   536.4 2499.33     612 2499.57   632.2 2497.07   664.4 2498.65
   684.6 2506.08   708.8 2507.87   728.9 2513.89   813.6  2530.5   834.7 2536.36
#Mann= 9 ,-1,0
       0      .1       0   131.9     .08       0   335.7    .045       0
  349.11     .08       0   387.4      .1       0   395.9     .08       0
   525.9      .1       0   536.4     .08       0   728.9      .1       0
#XS Ineff= 2 , 0
                          413.99            2505
Permanent Ineff=
       F       F
Bank Sta=335.7,349.11
XS Rating Curve= 0 ,0
Exp/Cntr(USF)=0,0
Exp/Cntr=0.5,0.3
LCMann Table=0

Chan Stop Cuts=-1
Use User Specified Reach Order=0
Composite Channel Slope=5